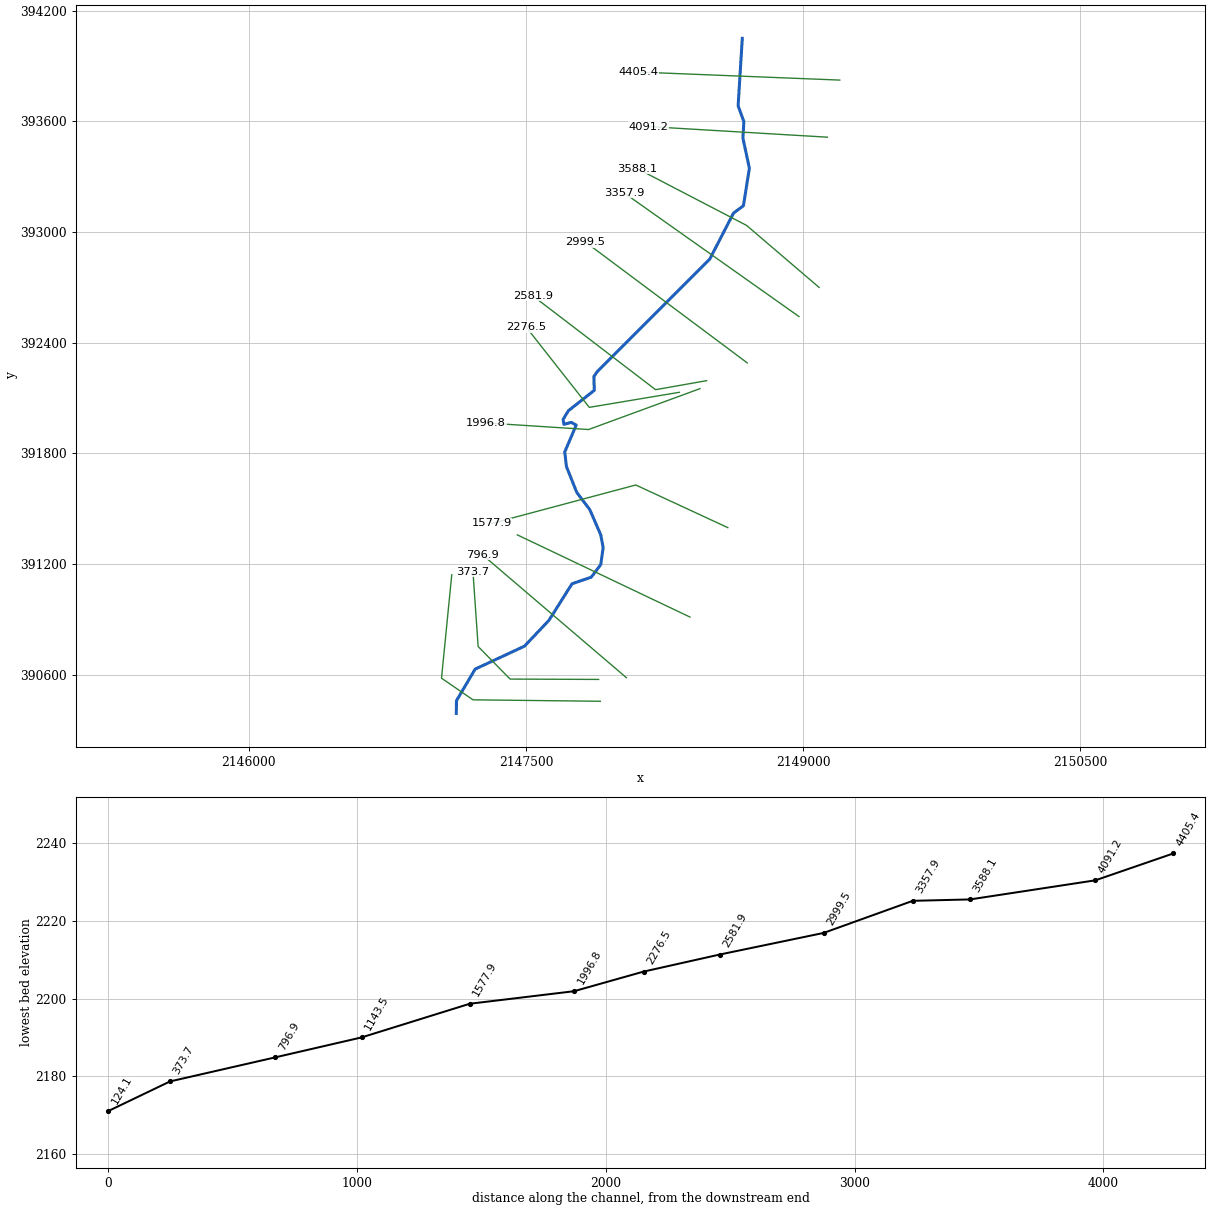
--- RockcmpRun.prj (project) ---

Proj Title=RockcmpRun
Current Plan=p01
Geom File=g01
Flow File=f01
Plan File=p01
DSS Export Rating Curves=0
DSS Export Rating Curve Sorted=0
DSS Export Volume Flow Curves=0
DXF OffsetX=0
DXF OffsetY=0
DXF ScaleX=0
DXF ScaleY=0

--- RockcmpRun.p01 (plan) ---

Plan Title=Floodplain
Program Version=4.00
Geom File=g01
Flow File=f01
K Sum by GR=0
Std Step Tol=0.01
Critical Tol=0.01
Num of Std Step Trials=20
Max Error Tol=0.3
Flow Tol Ratio=0.001
Split Flow NTrial=30
Split Flow Tol=0.02
Split Flow Ratio=0.02
Log Output Level=0
Friction Slope Method=1
Unsteady Friction Slope Method=2
Unsteady Bridges Friction Slope Method=1
Global Log Level=0
CheckData=False
Run HTab=0
Run UNet=0
Run PostProcess=0
UNET Theta=0
UNET Theta Warmup=0
UNET ZTol=0
UNET ZSATol=0
UNET MxIter=0
UNET MaxInSteps=0
UNET DtIC=0
UNET DtMin=0
UNET MaxCRTS=0
UNET WFStab=0
UNET SFStab=0
UNET WFX=0
UNET SFX=0
UNET DSS MLevel=0
UNET DZMax Abort=0
UNET Convert EG Bridges=0
UNET Use Existing IB Tables=0
UNET Froude Limit=0
UNET Froude Power=0
Write IC File=0
Echo Input=False
Echo Output=False
Write Detailed=0

--- RockcmpRun.f01 (steady flow) ---

Flow Title=NFF Regression Equation
Program Version=4.00
Number of Profiles=1
Profile Names=P100yr
River Rch & RM=RockcmpRun,Main      ,4405.4
492.1333
River Rch & RM=RockcmpRun,Main      ,4091.2
543.8262
River Rch & RM=RockcmpRun,Main      ,1577.9
584.3071
River Rch & RM=RockcmpRun,Main      ,1143.5
686.4870
River Rch & RM=RockcmpRun,Main      ,124.1
694.1842
Boundary for River Rch & Prof#=RockcmpRun,Main      ,1
Up Type=0
Dn Type=3
Dn Slope=0.019671

--- RockcmpRun.g01 (geometry) ---

Geom Title=USGS 10m DEM
Program Version=4.10

River Reach=RockcmpRun      ,Main
Reach XY= 30
     2148671.089       394050.34     2148648.496      393684.543
     2148679.628      393598.927      2148674.44       393509.42
     2148709.464      393345.972     2148677.034      393142.311
     2148623.849      393103.395      2148495.38      392854.255
       2147887.6      392244.917     2147867.919      392217.441
     2147870.172      392142.166      2147730.15      392031.736
       2147701.7      391985.164     2147705.427      391957.963
      2147745.64       391968.34     2147772.425       391953.67
     2147710.299      391808.447     2147719.506      391728.942
     2147775.627      391588.202     2147845.525      391496.157
     2147905.197      391358.653     2147918.169      391289.902
     2147905.197        391197.8     2147853.729      391129.382
     2147749.466      391093.346     2147625.001      390895.551
     2147492.686      390755.453     2147225.461      390630.921
     2147124.279       390459.69     2147123.511      390390.929

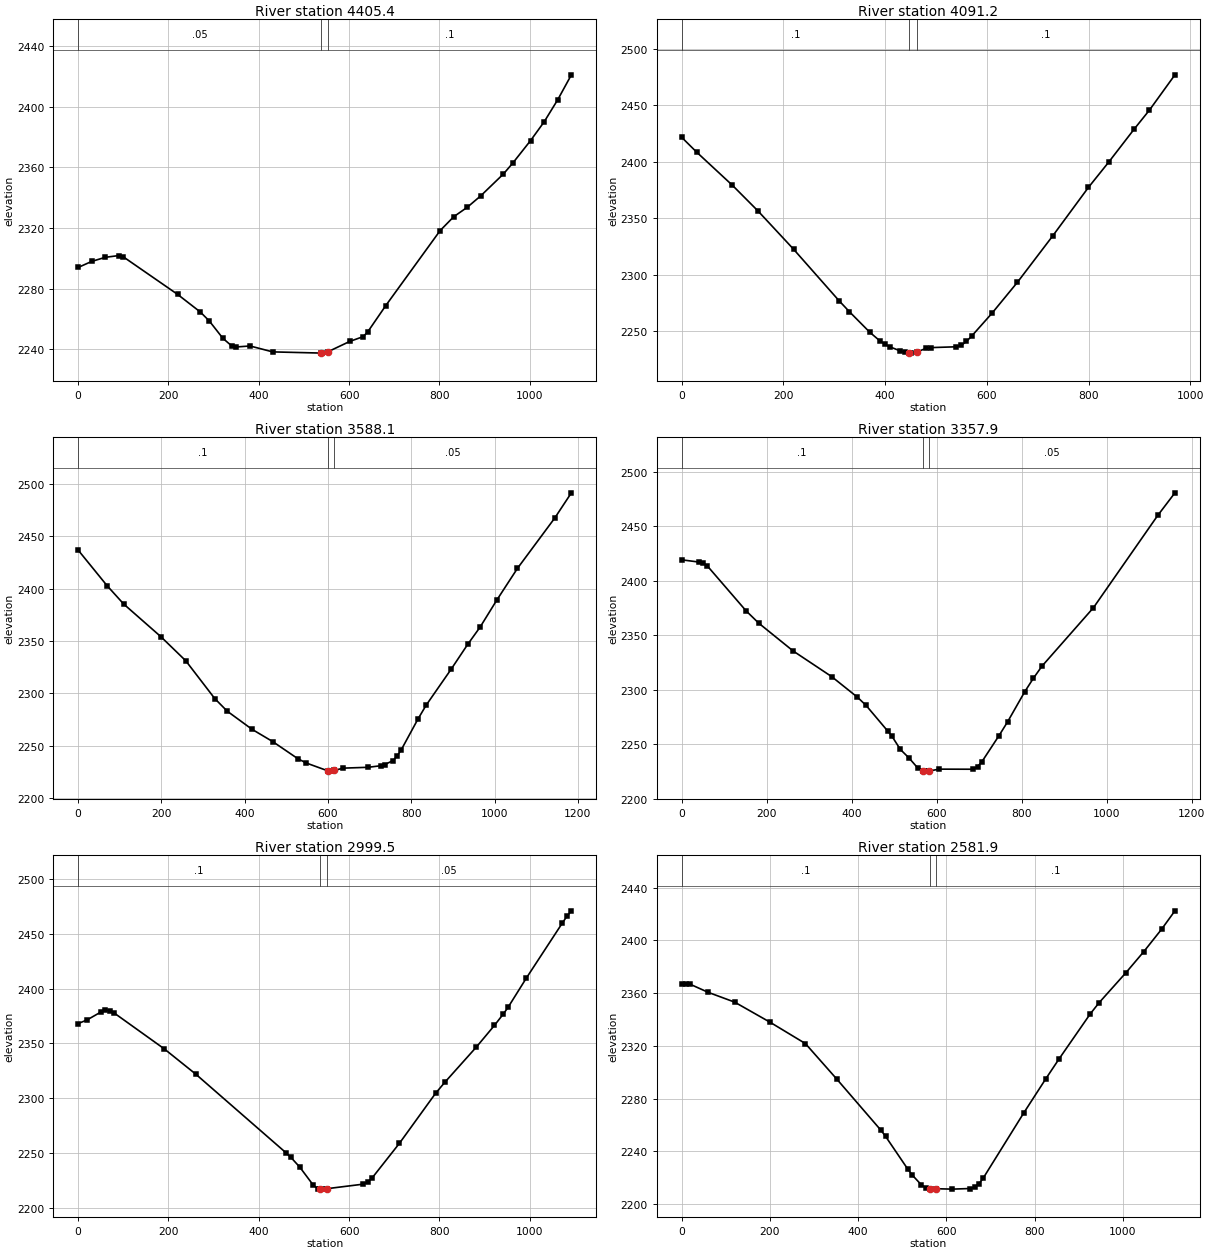
Type RM Length L Ch R = 1 ,4405.4  ,314.2,314.1,313.4
XS GIS Cut Line= 2
     2149198.848      393823.958     2148107.721      393867.605
#Sta/Elev= 30
       0 2293.88    30.1 2297.88    60.1 2300.58    90.2 2301.74   100.2 2300.89
   220.4 2276.13   270.5 2264.56   290.5 2258.62   320.6 2247.17   340.6 2242.05
   350.6 2241.49   380.7 2242.13   430.8 2238.24   538.5 2237.45     541 2237.42
   553.5 2238.37   601.1  2245.1   631.2 2248.31   641.2 2251.44   681.2 2268.79
   801.5 2318.22   831.5 2327.33   861.6 2333.59   891.6 2341.18   941.7 2355.57
   961.8 2362.53  1001.8  2377.6  1031.9 2389.98  1061.9 2404.53    1092  2420.9
#Mann= 3 , 0 , 0
       0     .05       0   538.5    .045       0   553.5      .1       0
Bank Sta=538.5,553.5
XS Rating Curve= 0 ,0
Exp/Cntr=0.3,0.1

Type RM Length L Ch R = 1 ,4091.2  ,513,503.1,493.2
XS GIS Cut Line= 2
     2149131.633      393514.474     2148163.428      393572.106
#Sta/Elev= 30
       0 2421.81      30 2408.45     100 2379.18     150 2356.55     220 2322.63
     310 2276.68     330 2267.14     370 2248.96     390 2241.26     400 2238.33
     410 2235.97     430 2232.41     440  2231.1   447.5 2230.64     450 2230.48
   462.5 2231.54     480  2234.6     490 2235.37     540  2236.1     550 2237.45
     560 2240.83     570 2245.46     610 2265.72     660 2293.16   729.9 2334.56
   799.9 2377.42   839.9 2399.91   889.9 2429.13   919.9 2445.96   969.9 2477.17
#Mann= 3 , 0 , 0
       0      .1       0   447.5    .045       0   462.5      .1       0
Bank Sta=447.5,462.5
XS Rating Curve= 0 ,0
Exp/Cntr=0.3,0.1

Type RM Length L Ch R = 1 ,3588.1  ,233.2,230.2,227
XS GIS Cut Line= 3
     2149086.792      392700.004     2148694.096      393036.332
     2148102.233      393344.477
#Sta/Elev= 30
       0 2436.91    69.6 2402.81   109.4  2385.3   198.9 2354.01   258.5 2331.04
   328.1 2294.94     358 2282.88   417.6 2265.54   467.3 2253.79     527  2237.6
   546.9 2233.46   600.4 2225.72   606.7 2225.56   615.4 2226.28   636.6 2228.42
   696.3 2229.22   726.2 2230.69   736.1 2231.76   756.1 2235.66     766 2240.05
     776 2246.03   815.8 2275.21   835.7  2288.6   895.5 2322.88   935.3 2346.66
   965.2 2363.23    1005 2388.88  1054.8 2419.34  1144.5 2467.52  1184.3 2491.56
#Mann= 3 , 0 , 0
       0      .1       0   600.4    .045       0   615.4     .05       0
Bank Sta=600.4,615.4
XS Rating Curve= 0 ,0
Exp/Cntr=0.3,0.1

Type RM Length L Ch R = 1 ,3357.9  ,358.9,358.4,357.7
XS GIS Cut Line= 2
     2148977.814      392542.174     2148030.834      393212.952
#Sta/Elev= 30
       0 2419.33    40.4 2417.28    50.5 2416.13    60.6 2413.65   151.4 2372.55
   181.6 2361.06   262.4 2335.56   353.2 2311.96   413.7 2293.07   433.9 2285.58
   484.4 2262.22   494.5 2257.41   514.6 2245.11   534.8 2237.33     555 2228.29
   566.9 2225.49   575.2  2225.2   581.9 2225.23   605.5 2227.03   686.2 2226.94
   696.3 2229.34   706.4 2233.86   746.7 2257.83   766.9 2270.55   807.3 2298.22
   827.5 2310.49   847.6 2321.58   968.8 2375.34  1120.1 2460.12  1160.5 2480.87
#Mann= 3 , 0 , 0
       0      .1       0   566.9    .045       0   581.9     .05       0
Bank Sta=566.9,581.9
XS Rating Curve= 0 ,0
Exp/Cntr=0.3,0.1

Type RM Length L Ch R = 1 ,2999.5  ,417.9,417.7,417.4
XS GIS Cut Line= 2
     2148697.713      392291.054     2147823.222      392945.279
#Sta/Elev= 30
       0 2368.02      20 2371.43    50.1 2378.52    60.1 2380.11    70.1 2379.92
    80.2 2377.62   190.4  2345.1   260.5 2321.91   460.9 2249.89   470.9 2246.03
     491 2236.91     521 2220.39     531 2217.39   536.2 2217.15     541 2216.92
   551.2 2217.34   631.2 2221.45   641.2 2223.41   651.3  2227.3   711.4 2258.74
   791.5 2304.42   811.6  2314.3   881.7 2346.61   921.8 2366.41   941.8    2377
   951.9 2382.86   991.9 2409.27  1072.1 2459.85  1082.1 2465.94  1092.1    2471
#Mann= 3 , 0 , 0
       0      .1       0   536.2    .045       0   551.2     .05       0
Bank Sta=536.2,551.2
XS Rating Curve= 0 ,0
Exp/Cntr=0.3,0.1

Type RM Length L Ch R = 1 ,2581.9  ,309.1,305.4,299.9
XS GIS Cut Line= 3
     2148478.019      392194.572     2148201.816       392145.72
     2147536.675       392654.91
#Sta/Elev= 30
       0 2366.99      10 2367.22      20  2366.6    60.1 2360.58   120.2 2353.14
   200.4 2337.91   280.5 2321.73   351.1 2295.01   452.1 2255.86   462.2 2251.39
   512.6 2226.54   522.7 2222.05   542.9 2214.77     553 2212.34   562.7 2211.65
   577.7 2211.65   613.5 2211.35   653.9 2211.81     664 2212.82   674.1 2215.36
   684.2 2220.01     775 2268.85   825.5 2295.02   855.8  2310.2   926.4  2344.3
   946.6 2352.81  1007.1 2375.44  1047.5 2391.38  1087.9 2408.38  1118.2 2422.37
#Mann= 3 , 0 , 0
       0      .1       0   562.7    .045       0   577.7      .1       0
Bank Sta=562.7,577.7
XS Rating Curve= 0 ,0
Exp/Cntr=0.3,0.1

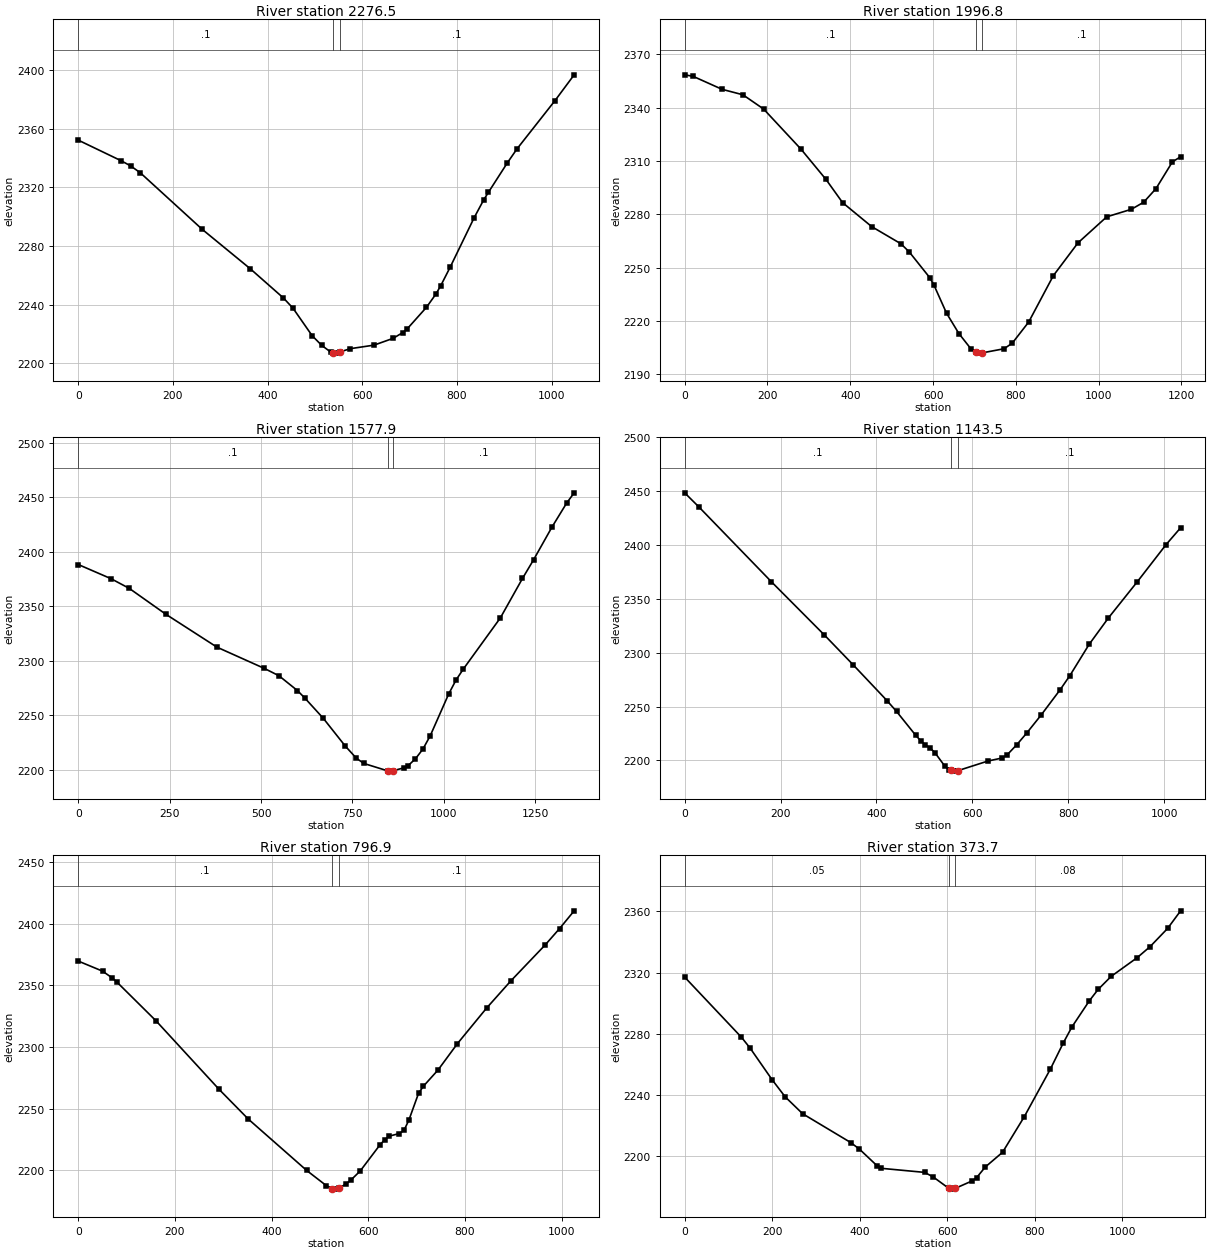
Type RM Length L Ch R = 1 ,2276.5  ,238,279.7,223.6
XS GIS Cut Line= 3
     2148330.377      392131.503     2147843.069      392049.843
     2147501.384      392485.236
#Sta/Elev= 30
       0 2352.13    90.8 2338.05   110.9 2334.52   131.1 2329.88   262.2 2291.25
     363 2264.58   433.6 2244.51   453.8 2237.54   494.1 2218.87   514.2 2212.29
   534.4 2207.45   537.7 2207.29   544.4 2206.96   552.7 2207.75   574.6 2209.99
   624.9 2212.41   665.2 2217.04   685.3 2220.91   695.4 2223.66   735.6 2238.18
   755.7 2247.27   765.8 2252.93   785.9 2265.66   836.2 2299.15   856.4 2311.34
   866.4 2316.51   906.7 2336.74   926.8 2346.12  1007.3 2379.12  1047.6 2396.62
#Mann= 3 , 0 , 0
       0      .1       0   537.7    .045       0   552.7      .1       0
Bank Sta=537.7,552.7
XS Rating Curve= 0 ,0
Exp/Cntr=0.3,0.1

Type RM Length L Ch R = 1 ,1996.8  ,411.9,418.9,499.4
XS GIS Cut Line= 3
     2148442.319      392151.357     2147839.183      391929.643
     2147284.899      391965.343
#Sta/Elev= 30
       0 2358.49    20.1 2357.67    90.4 2350.33   140.6 2347.27   190.8 2339.22
   281.1 2316.64   341.4 2299.62   381.5 2286.57   451.8 2273.08   522.1 2263.46
   542.2 2258.92   592.4 2244.26   602.4 2240.05   632.6 2224.35   662.4 2212.92
   692.2  2204.1     704 2202.26     712  2201.9     719 2202.06   771.5 2204.36
   791.4 2207.53     831  2219.4   890.6 2245.51   950.1 2263.95  1019.5 2278.59
    1079 2282.83  1108.8 2286.81  1138.5 2294.47  1178.2 2309.53    1198 2312.39
#Mann= 3 , 0 , 0
       0      .1       0     704    .045       0     719      .1       0
Bank Sta=704,719
XS Rating Curve= 0 ,0
Exp/Cntr=0.3,0.1

Type RM Length L Ch R = 1 ,1577.9  ,449.8,434.3,419
XS GIS Cut Line= 3
     2148592.633      391397.906     2148094.717      391629.015
     2147314.962      391420.454
#Sta/Elev= 30
       0 2388.41    89.8 2375.37   139.7 2366.46   239.5 2342.76   379.3 2312.52
     509 2292.98   548.9 2286.25   599.4 2272.66   619.6  2265.8     670 2247.23
   730.6 2221.54   760.8 2210.47     781 2205.72   846.2 2198.92   851.6 2198.67
   861.2 2199.03     892 2201.84   902.1 2203.67   922.2 2210.04   942.4 2218.82
   962.6 2231.17  1013.1 2269.57  1033.2  2282.4  1053.4 2292.56  1154.3 2339.37
  1214.8  2375.6  1245.1 2392.72  1295.6 2422.87  1335.9 2444.99  1356.1 2454.23
#Mann= 3 , 0 , 0
       0      .1       0   846.2    .045       0   861.2      .1       0
Bank Sta=846.2,861.2
XS Rating Curve= 0 ,0
Exp/Cntr=0.3,0.1

Type RM Length L Ch R = 1 ,1143.5  ,351.8,346.7,339.9
XS GIS Cut Line= 2
      2148387.83      390913.143     2147454.003      391358.449
#Sta/Elev= 30
       0 2448.49    30.1 2435.18   180.8 2365.94   291.3 2316.49   351.6 2288.68
   421.9 2255.58     442 2245.41   482.1 2223.18   492.2 2218.32   502.2 2214.47
   512.3 2211.34   522.3 2206.99   542.4 2194.81   552.4 2190.93   555.4 2190.65
   562.5    2190   570.4  2190.5   632.8  2199.4   662.9 2202.26     673 2205.27
   693.1 2214.67   713.2 2225.17   743.3 2241.92   783.5 2265.73   803.6 2278.73
   843.7  2307.7   883.9 2332.26   944.2 2365.88  1004.4 2400.48  1034.6 2416.02
#Mann= 3 , 0 , 0
       0      .1       0   555.4    .045       0   570.4      .1       0
Bank Sta=555.4,570.4
XS Rating Curve= 0 ,0
Exp/Cntr=0.3,0.1

Type RM Length L Ch R = 1 ,796.9   ,424.8,423.2,422.1
XS GIS Cut Line= 2
     2148043.986       390584.33     2147264.231       391251.35
#Sta/Elev= 30
       0 2369.63    50.3 2361.46    70.4 2355.95    80.5 2352.42     161  2321.2
   291.7 2265.59   352.1 2241.53   472.8 2199.96   513.1 2187.77   525.1 2185.34
   533.2 2184.86   540.1 2185.83   553.3 2188.84   563.4 2191.92   583.5 2199.58
   623.7 2220.39   633.8 2224.84   643.8 2227.84     664 2229.84     674 2232.45
   684.1 2240.73   704.2 2262.53   714.3 2268.29   744.4 2281.34   784.7  2302.8
     845 2331.57   895.3 2353.65   965.8 2382.54     996 2395.98  1026.1 2410.32
#Mann= 3 , 0 , 0
       0      .1       0   525.1    .045       0   540.1      .1       0
Bank Sta=525.1,540.1
XS Rating Curve= 0 ,0
Exp/Cntr=0.3,0.1

Type RM Length L Ch R = 1 ,373.7   ,245,249.6,253.1
XS GIS Cut Line= 4
     2147893.672      390574.936     2147414.545      390576.815
     2147241.684      390753.434       2147213.5      391159.283
#Sta/Elev= 30
       0 2317.09   129.8  2277.8   149.7 2270.66   199.6 2250.15   229.6 2238.92
   269.5 2227.88   379.3 2209.08   399.3 2204.76   439.2    2194   449.2 2192.24
   548.3 2189.58   568.1 2186.54   603.7 2179.11   607.6 2178.65   618.7 2179.21
   657.1 2184.07     667 2186.15   686.7 2193.06   726.3 2202.72   775.9 2225.94
   835.4 2256.96   865.2 2274.22     885 2284.67   924.7 2301.69   944.6 2309.05
   974.3 2317.55  1033.9  2329.8  1063.6 2337.07  1103.3 2348.86  1133.1 2360.38
#Mann= 3 , 0 , 0
       0     .05       0   603.7    .045       0   618.7     .08       0
Bank Sta=603.7,618.7
XS Rating Curve= 0 ,0
Exp/Cntr=0.3,0.1

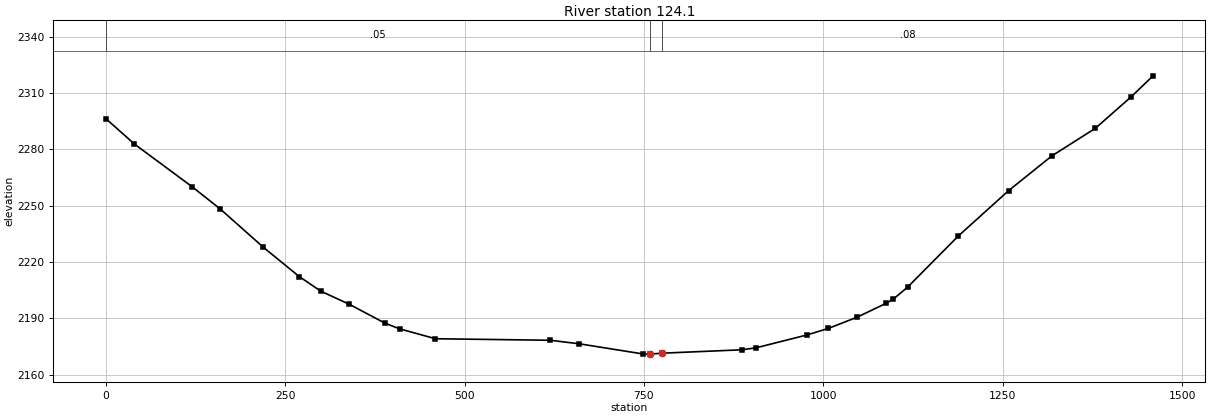
Type RM Length L Ch R = 1 ,124.1   ,110.6,124.1,137.5
XS GIS Cut Line= 4
     2147903.067      390456.563     2147213.821      390464.393
     2147043.431      390581.773     2147098.885      391142.372
#Sta/Elev= 30
       0 2296.37      40 2282.78   119.9  2260.2   159.8 2248.14   219.8 2227.78
   269.7 2212.24   299.7 2204.49   339.6 2197.46   389.6 2187.35   409.6 2184.42
   459.5 2179.16   619.4 2178.35   659.3  2176.5   748.4 2171.08   758.3 2170.97
   774.7 2171.46   886.4 2173.28   906.3 2174.34   976.7 2181.13  1006.8 2184.62
  1047.1 2190.64  1087.3 2197.98  1097.4 2200.23  1117.5 2206.64  1187.9 2233.78
  1258.3 2258.04  1318.7 2276.56  1379.1 2291.18  1429.4 2308.09  1459.5 2319.12
#Mann= 3 , 0 , 0
       0     .05       0   758.3    .045       0   774.7     .08       0
Bank Sta=758.3,774.7
XS Rating Curve= 0 ,0
Exp/Cntr=0.3,0.1

Chan Stop Cuts=-1
Use User Specified Reach Order=0
Composite Channel Slope=5